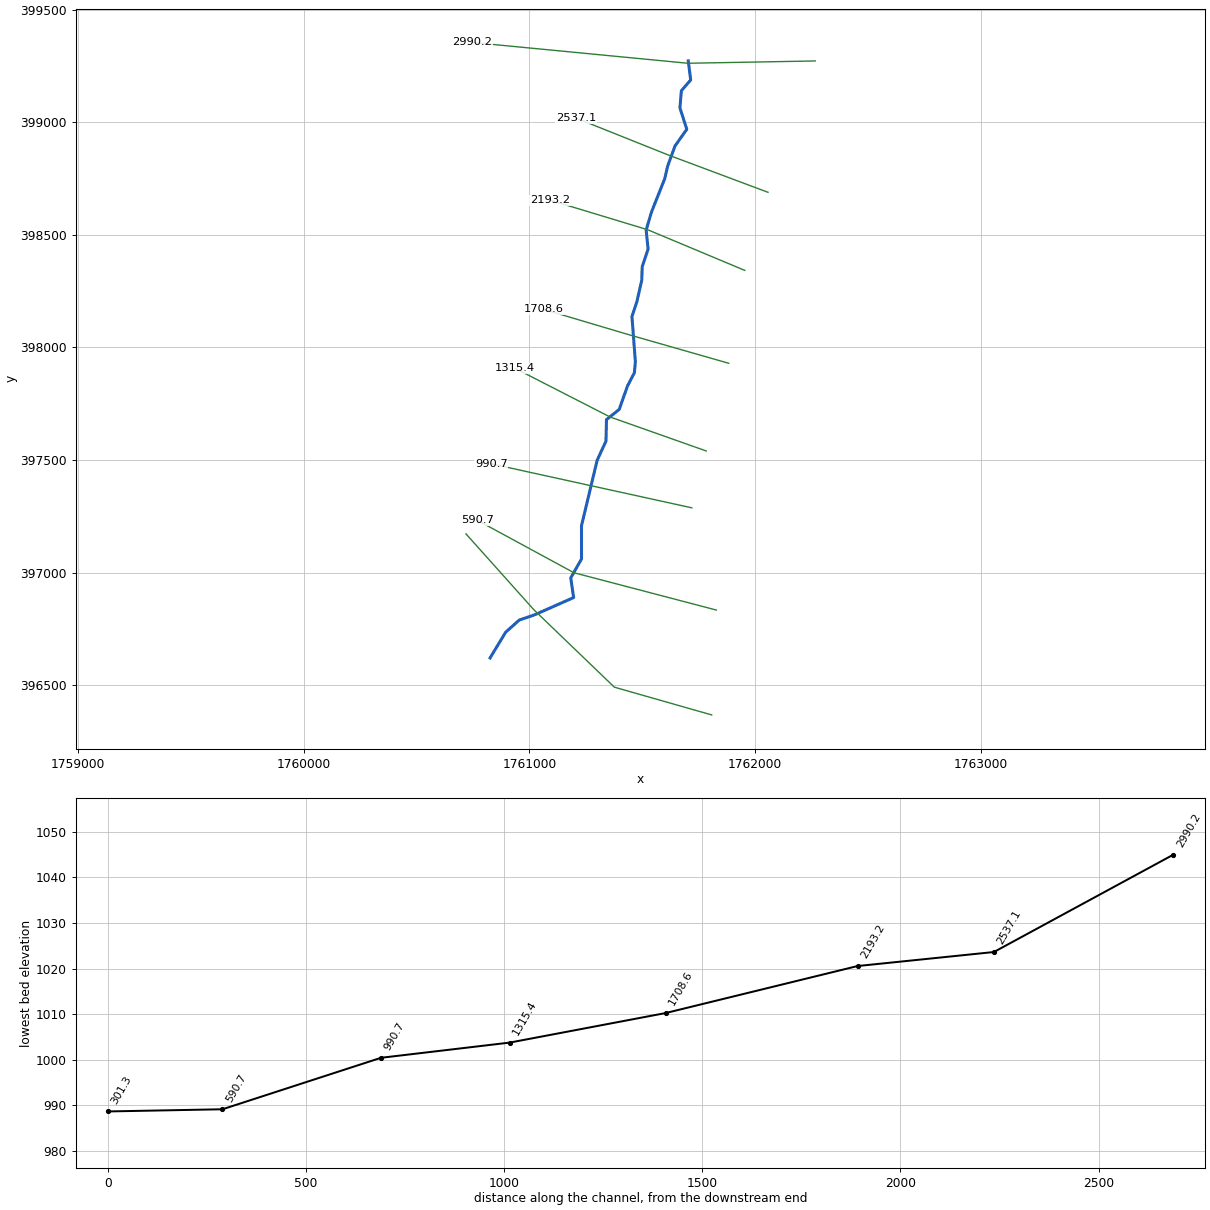
--- RshRn.prj (project) ---

Proj Title=RshRn
Current Plan=p01
Geom File=g01
Flow File=f01
Plan File=p01
DSS Export Rating Curves=0
DSS Export Rating Curve Sorted=0
DSS Export Volume Flow Curves=0
DXF OffsetX=0
DXF OffsetY=0
DXF ScaleX=0
DXF ScaleY=0

--- RshRn.p01 (plan) ---

Plan Title=Floodplain
Program Version=4.00
Geom File=g01
Flow File=f01
K Sum by GR=0
Std Step Tol=0.01
Critical Tol=0.01
Num of Std Step Trials=20
Max Error Tol=0.3
Flow Tol Ratio=0.001
Split Flow NTrial=30
Split Flow Tol=0.02
Split Flow Ratio=0.02
Log Output Level=0
Friction Slope Method=1
Unsteady Friction Slope Method=2
Unsteady Bridges Friction Slope Method=1
Global Log Level=0
CheckData=False
Run HTab=0
Run UNet=0
Run PostProcess=0
UNET Theta=0
UNET Theta Warmup=0
UNET ZTol=0
UNET ZSATol=0
UNET MxIter=0
UNET MaxInSteps=0
UNET DtIC=0
UNET DtMin=0
UNET MaxCRTS=0
UNET WFStab=0
UNET SFStab=0
UNET WFX=0
UNET SFX=0
UNET DSS MLevel=0
UNET DZMax Abort=0
UNET Convert EG Bridges=0
UNET Use Existing IB Tables=0
UNET Froude Limit=0
UNET Froude Power=0
Write IC File=0
Echo Input=False
Echo Output=False
Write Detailed=0

--- RshRn.f01 (steady flow) ---

Flow Title=NFF Regression Equation
Program Version=4.00
Number of Profiles=1
Profile Names=P100yr
River Rch & RM=RshRn,Main      ,2990.2
734.7888
River Rch & RM=RshRn,Main      ,301.3
792.5736
Boundary for River Rch & Prof#=RshRn,Main      ,1
Up Type=0
Dn Type=3
Dn Slope=0.012091

--- RshRn.g01 (geometry) ---

Geom Title=USGS 3m DEM
Program Version=4.00

River Reach=RshRn     ,Main
Reach XY= 30
     1761704.068      399272.231     1761714.919      399187.596
     1761673.686      399139.853     1761667.176      399063.898
     1761697.558      398968.412     1761645.474      398894.627
     1761612.922      398805.652     1761599.901      398749.228
     1761541.308      398601.658     1761517.436      398521.363
     1761526.117      398436.728     1761500.075      398358.603
     1761497.905      398297.839     1761476.203      398202.353
     1761454.502      398137.249     1761469.693      397937.596
     1761465.353      397887.683     1761434.971      397829.089
     1761398.078      397724.922     1761341.655      397679.349
     1761339.485      397583.863     1761300.422      397499.228
     1761230.978      397208.429     1761230.978      397060.860
     1761183.235      396976.224     1761196.255      396889.419
     1761024.814      396813.464     1760955.370      396789.593
     1760894.606      396735.339     1760825.862      396621.317

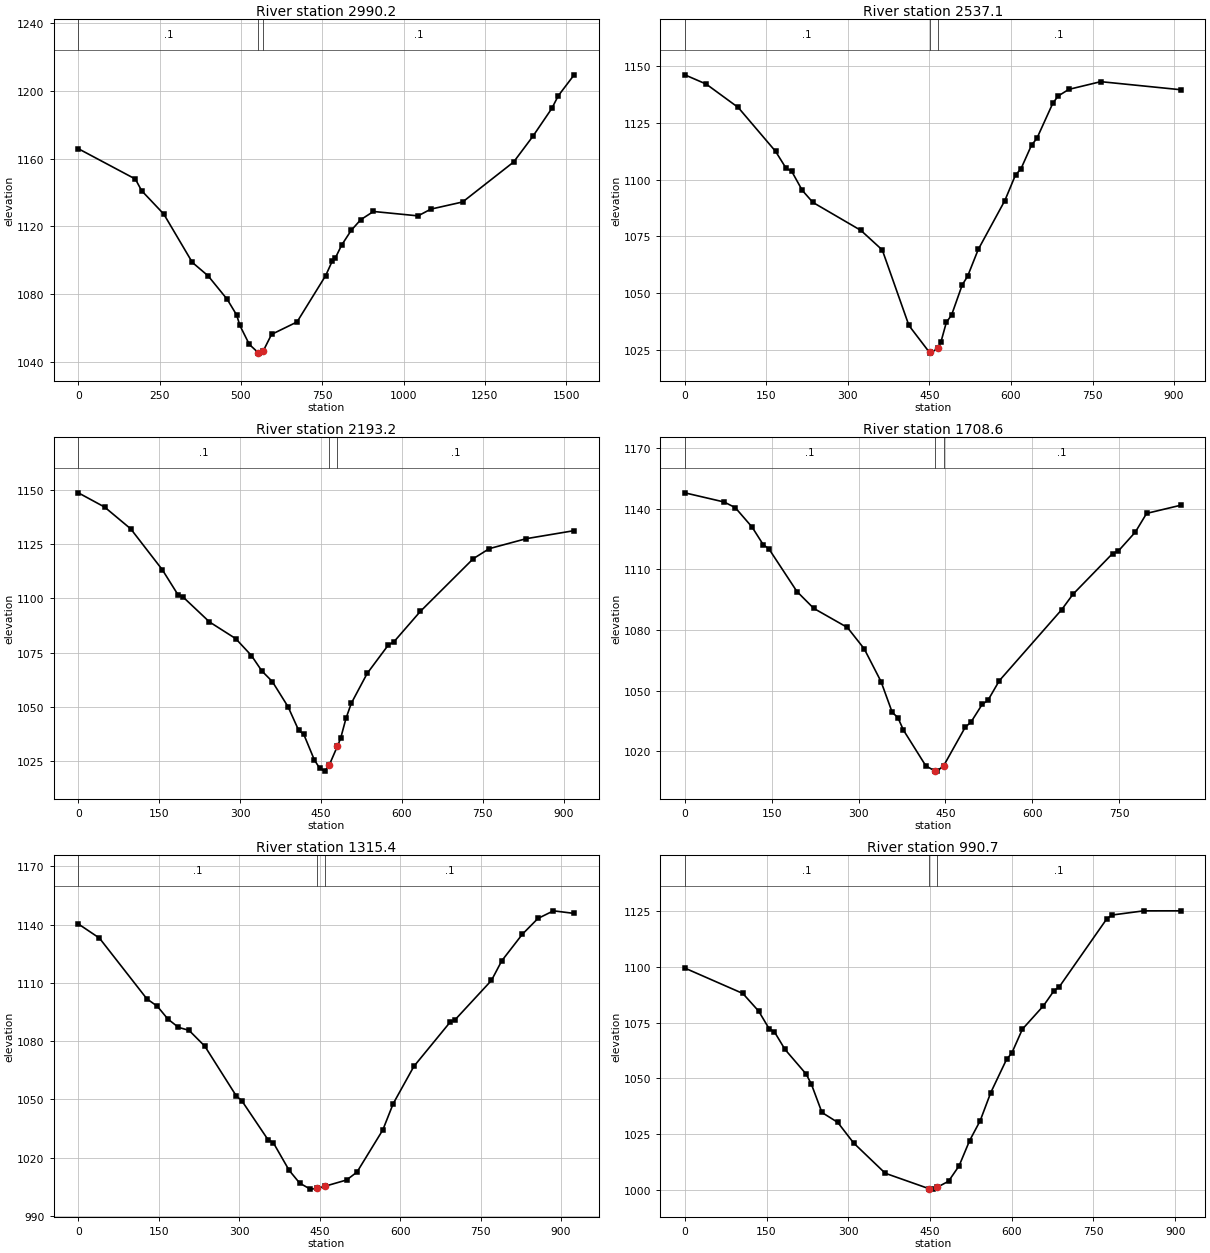
Type RM Length L Ch R = 1 ,2990.2,463.08,453.074,445.092
XS GIS Cut Line= 3
     1762266.788      399271.881     1761702.109      399261.676
     1760746.511      399354.058
#Sta/Elev= 30
       0 1165.83   175.3 1147.90   194.7 1141.00   262.9 1127.14   350.5 1098.62
   399.2 1090.64   457.7 1076.82   486.9 1067.52   496.6 1061.40   525.8 1050.16
     554 1045.09   555.0 1044.98     569 1046.40   594.2 1056.06   672.5 1063.40
   760.7 1090.83   780.3 1099.15   790.1 1101.13   809.7 1108.81   839.1 1117.54
   868.5 1123.87   907.6 1128.72  1044.8 1126.12  1084.0 1130.10  1181.9 1134.34
  1338.7 1157.96  1397.5 1173.06  1456.2 1189.67  1475.8 1197.08  1524.8 1209.50
#Mann= 3 , 0 , 0
       0     0.1       0     554   0.045       0     569     0.1       0
Bank Sta=     554,     569
Exp/Cntr=0.3,0.1

Type RM Length L Ch R = 1 ,2537.1,344.558,343.903,345.542
XS GIS Cut Line= 3
     1762057.495      398688.747     1761616.219      398854.147
     1761206.977      399018.059
#Sta/Elev= 30
       0 1146.17    39.3 1142.11    98.2 1131.81   166.9 1112.50   186.5 1104.96
   196.4 1103.80   216.0 1095.33   235.6 1090.00   324.0 1077.66   363.3 1069.05
   412.3 1035.80   450.2 1023.91   451.6 1023.63   465.2 1025.73   471.3 1028.64
   481.1 1037.15   490.8 1040.44   510.4 1053.71   520.2 1057.45   539.8 1069.28
   588.8 1090.83   608.4 1102.12   618.2 1104.68   637.8 1115.20   647.6 1118.15
   677.0 1133.66   686.8 1136.84   706.4 1139.76   765.2 1143.16   912.1 1139.61
#Mann= 3 , 0 , 0
       0     0.1       0   450.2   0.045       0   465.2     0.1       0
Bank Sta=   450.2,   465.2
Exp/Cntr=0.3,0.1

Type RM Length L Ch R = 1 ,2193.2,482.428,484.622,484.723
XS GIS Cut Line= 3
     1761954.644      398342.032     1761524.272      398522.547
     1761091.174      398653.953
#Sta/Elev= 30
       0 1148.59    48.6 1142.06    97.2 1132.00   155.6 1113.25   184.7 1101.72
   194.5 1100.58   243.1 1089.20   291.7 1081.53   320.9 1073.74   340.3 1066.63
   359.7 1061.76   388.9 1050.15   408.4 1039.39   418.1 1037.42   437.5 1025.78
   447.3 1021.95   457.0 1020.56   465.4 1023.46   480.4 1032.04   486.4 1035.71
   496.2 1044.79   506.1 1051.77   535.6 1065.53   574.9 1078.63   584.8 1079.96
   634.0 1094.01   732.3 1118.30   761.9 1122.91   830.7 1127.51   919.3 1131.19
#Mann= 3 , 0 , 0
       0     0.1       0   465.4   0.045       0   480.4     0.1       0
Bank Sta=   465.4,   480.4
Exp/Cntr=0.3,0.1

Type RM Length L Ch R = 1 ,1708.6,393.372,393.201,389.329
XS GIS Cut Line= 3
     1761883.295      397929.654     1761436.686      398057.685
     1761061.523      398169.337
#Sta/Elev= 30
       0 1147.90    67.8 1143.37    87.1 1140.58   116.1 1130.98   135.5 1122.22
   145.2 1120.18   193.6 1099.09   222.6 1090.76   280.7 1081.30   309.7 1070.77
   338.8 1054.53   358.1 1039.30   367.8 1036.77   377.5 1030.52   416.2 1012.82
     432 1010.32   435.6 1010.25     447 1012.96   484.2 1031.99   494.0 1034.47
   513.5 1043.29   523.3 1045.24   542.9 1054.95   650.5 1090.06   670.1 1097.72
   738.6 1117.89   748.4 1119.10   777.7 1128.44   797.3 1137.73   856.0 1141.75
#Mann= 3 , 0 , 0
       0     0.1       0     432   0.045       0     447     0.1       0
Bank Sta=     432,     447
Exp/Cntr=0.3,0.1

Type RM Length L Ch R = 1 ,1315.4,321.898,324.619,331.017
XS GIS Cut Line= 3
     1761783.595      397540.277     1761357.585      397691.155
     1760937.259      397906.659
#Sta/Elev= 30
       0 1140.34    39.3 1133.05   127.7 1101.78   147.4 1097.90   167.0 1091.35
   186.7 1087.07   206.3 1085.56   235.8 1077.38   294.7 1051.66   304.6 1049.35
   353.7 1029.19   363.5 1027.67   393.0 1013.46   412.6 1006.88   432.3 1003.78
   445.3 1004.12   460.3 1005.31   500.1 1008.49   519.4 1012.54   567.6 1034.25
   586.9 1047.76   625.5 1066.99   692.9 1089.70   702.6 1091.08   770.1 1111.25
   789.3 1121.33   827.9 1135.09   856.8 1143.16   885.7 1147.09   924.3 1145.76
#Mann= 3 , 0 , 0
       0     0.1       0   445.3   0.045       0   460.3     0.1       0
Bank Sta=   445.3,   460.3
Exp/Cntr=0.3,0.1

Type RM Length L Ch R = 1 ,990.7,400.91,400,393.471
XS GIS Cut Line= 3
     1761719.820      397287.825     1761275.426      397385.494
     1760831.032      397483.163
#Sta/Elev= 30
       0 1099.37   106.5 1088.00   135.5 1080.12   154.9 1072.18   164.6 1070.78
   183.9 1062.96   222.7 1051.94   232.3 1047.44   251.7 1034.75   280.7 1030.31
   309.8 1021.11   367.9 1007.55   447.5 1000.71   455.0 1000.45   462.5 1001.19
   484.0 1003.97   503.4 1010.86   522.8 1022.20   542.1 1031.04   561.5 1043.62
   590.5 1058.49   600.2 1061.36   619.6 1072.03   658.3 1082.50   677.7 1089.26
   687.3 1090.97   774.5 1121.40   784.1 1123.10   842.2 1124.97   910.0 1124.98
#Mann= 3 , 0 , 0
       0     0.1       0   447.5   0.045       0   462.5     0.1       0
Bank Sta=   447.5,   462.5
Exp/Cntr=0.3,0.1

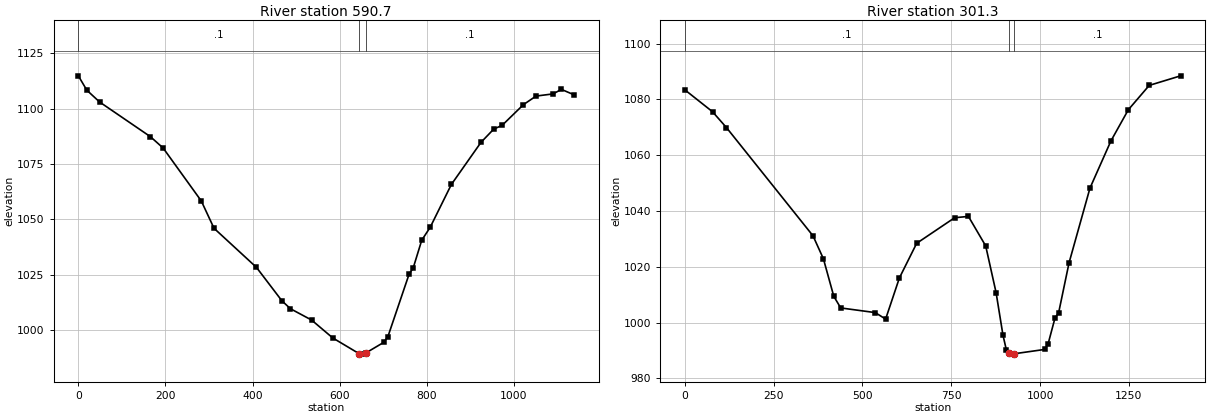
Type RM Length L Ch R = 1 ,590.7,302.516,289.448,279.642
XS GIS Cut Line= 3
     1761828.510      396833.958     1761197.599      396999.567
     1760770.639      397231.667
#Sta/Elev= 30
       0 1114.87    19.5 1108.38    48.7 1103.07   165.5 1087.38   194.7 1082.26
   282.3 1058.35   311.5 1046.01   408.9 1028.36   467.3 1013.27   486.8 1009.69
   535.5 1004.57   584.1  996.48   644.8  989.36   652.3  989.17   659.8  989.66
   700.9  994.46   710.6  997.02   759.2 1025.21   768.9 1028.16   788.4 1040.63
   807.8 1046.46   856.4 1065.80   924.4 1084.82   953.6 1090.80   973.0 1092.51
  1021.6 1101.82  1050.8 1105.73  1089.7 1106.70  1109.1 1108.74  1138.3 1106.27
#Mann= 3 , 0 , 0
       0     0.1       0   644.8   0.045       0   659.8     0.1       0
Bank Sta=   644.8,   659.8
Exp/Cntr=0.3,0.1

Type RM Length L Ch R = 1 ,301.3,296.571,301.291,306.047
XS GIS Cut Line= 4
     1761807.966      396368.288     1761376.536      396491.553
     1761019.747      396835.332     1760719.018      397172.150
#Sta/Elev= 30
       0 1083.45    78.0 1075.59   117.1 1069.93   360.9 1031.10   390.2 1022.85
   419.4 1009.41   438.9 1005.25   536.1 1003.58   565.3 1001.25   604.1 1016.02
   652.7 1028.42   759.6 1037.59   798.4 1038.06   847.0 1027.48   876.2 1010.78
   895.6  995.51   905.3  990.12   912.7  989.03   915.0  988.69   927.7  988.83
  1012.9  990.37  1022.7  992.37  1042.3 1001.76  1052.1 1003.39  1081.6 1021.41
  1140.5 1048.21  1199.4 1065.10  1248.5 1076.30  1307.3 1085.03  1395.7 1088.46
#Mann= 3 , 0 , 0
       0     0.1       0   912.7   0.045       0   927.7     0.1       0
Bank Sta=   912.7,   927.7
Exp/Cntr=0.3,0.1